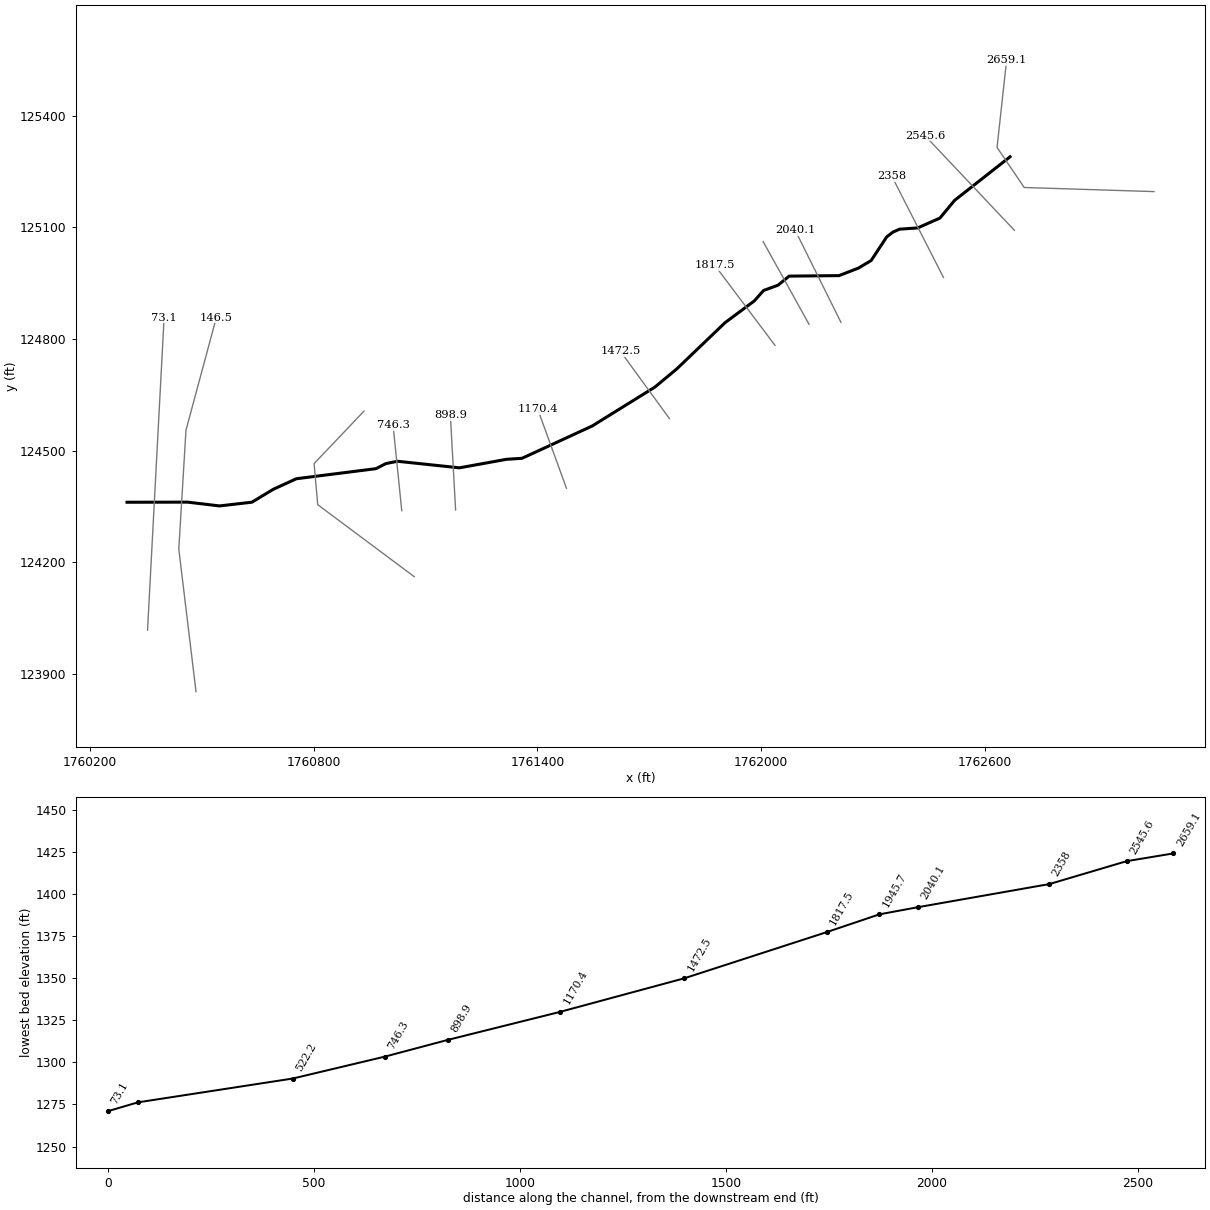
--- Threefork Branch.prj (project) ---

Proj Title=Threefork Branch
Current Plan=p01
Default Exp/Contr=0,0
English Units
Geom File=g01
Flow File=f01
Plan File=p01
BEGIN DESCRIPTION:
END DESCRIPTION:
DSS Export Rating Curves= 0
DSS Export Rating Curve Sorted= 0
DSS Export Volume Flow Curves= 0
DXF OffsetX= 0
DXF OffsetY= 0
DXF ScaleX= 0
DXF ScaleY= 0

--- Threefork Branch.p01 (plan) ---

Plan Title=Floodplain
Program Version=4.00
Geom File=g01
Flow File=f01
K Sum by GR=0
Std Step Tol=0.01
Critical Tol=0.01
Num of Std Step Trials=20
Max Error Tol=0.3
Flow Tol Ratio=0.001
Split Flow NTrial=30
Split Flow Tol=0.02
Split Flow Ratio=0.02
Log Output Level=0
Friction Slope Method=1
Unsteady Friction Slope Method=2
Unsteady Bridges Friction Slope Method=1
Global Log Level=0
CheckData=False
Run HTab=0
Run UNet=0
Run PostProcess=0
UNET Theta=0
UNET Theta Warmup=0
UNET ZTol=0
UNET ZSATol=0
UNET MxIter=0
UNET MaxInSteps=0
UNET DtIC=0
UNET DtMin=0
UNET MaxCRTS=0
UNET WFStab=0
UNET SFStab=0
UNET WFX=0
UNET SFX=0
UNET DSS MLevel=0
UNET DZMax Abort=0
UNET Convert EG Bridges=0
UNET Use Existing IB Tables=0
UNET Froude Limit=0
UNET Froude Power=0
Write IC File=0
Echo Input=False
Echo Output=False
Write Detailed=0

--- Threefork Branch.f01 (steady flow) ---

Flow Title=NFF Regression Equation
Program Version=4.00
Number of Profiles=1
Profile Names=P100yr
River Rch & RM=Threefork Branch,Main      ,2659.1
551.8075
River Rch & RM=Threefork Branch,Main      ,2358
581.6288
River Rch & RM=Threefork Branch,Main      ,146.5
626.7487
Boundary for River Rch & Prof#=Threefork Branch,Main      ,1
Up Type=0
Dn Type=3
Dn Slope=0.048855

--- Threefork Branch.g01 (geometry) ---

Geom Title=Geometry
Program Version=4.00

River Reach=Threefork Branch,Main
Reach XY= 30
     1762667.441      125289.327     1762518.508      125172.035
     1762479.462      125124.654      1762419.66      125098.173
     1762371.461      125094.862     1762353.759      125087.206
     1762336.696      125074.081     1762295.013      125010.573
     1762260.573      124990.082     1762208.754      124970.035
     1762075.281      124968.672      1762045.04      124944.213
      1762006.45      124930.085     1761981.942      124902.256
     1761903.204      124843.526     1761773.886      124719.422
     1761715.353      124670.627     1761546.777      124565.858
     1761358.927      124479.197     1761317.139       124476.48
     1761191.075      124453.607     1761025.092      124471.215
     1760993.806      124464.957     1760967.243      124451.352
     1760753.941      124424.285     1760692.411      124396.127
     1760634.767      124361.294     1760547.821      124351.248
     1760462.061      124361.437     1760299.856      124361.156

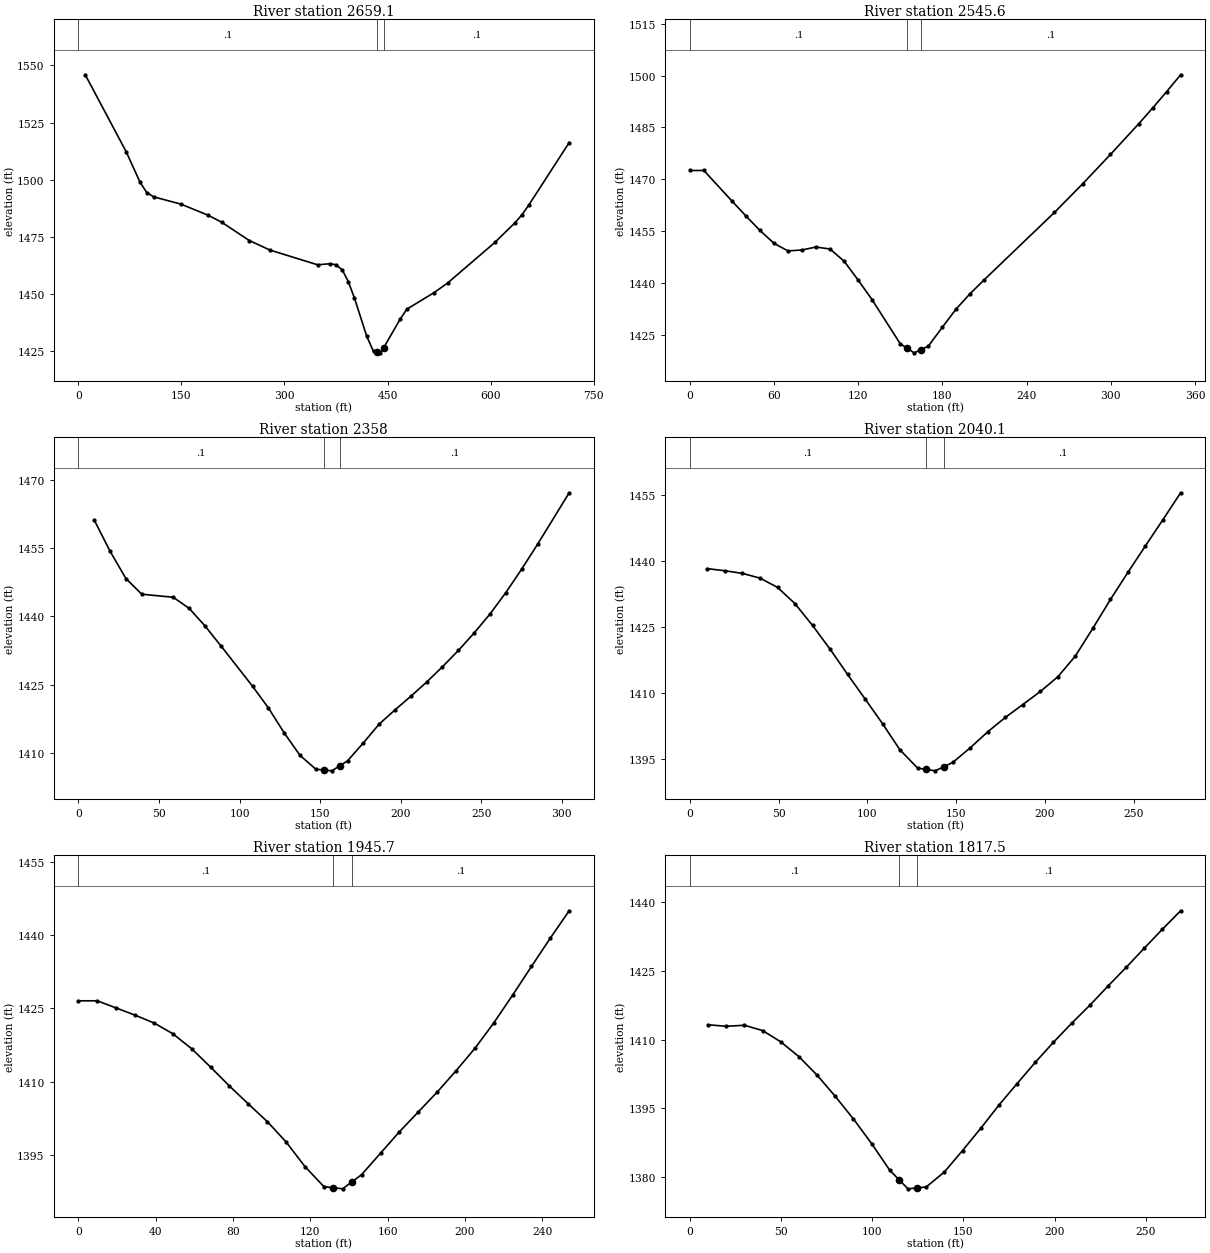
Type RM Length L Ch R = 1 ,2659.1  ,110.3,113.5,116.6
XS GIS Cut Line= 5
     1763053.546      125195.788     1762705.405      125206.801
     1762665.348      125266.015     1762632.573      125314.464
     1762658.199      125549.205
#Sta/Elev= 30
      10 1545.89    69.7 1512.17    89.6 1498.99    99.5  1494.4   109.5 1492.53
   149.3 1489.33   189.1 1484.45     209 1481.35   248.8 1473.42   278.7 1469.27
   348.3  1462.8   366.2 1463.28   375.1 1462.82   384.1 1460.56     393 1455.39
   401.9 1448.23   419.8 1431.49   429.6 1424.92   434.3 1424.63   439.3 1424.32
   444.3 1426.51   468.6 1439.17   478.3 1443.45   517.7 1450.63   537.3 1454.81
   606.2 1472.58   635.7 1481.24   645.6 1484.65   655.4 1488.83   714.4 1516.23
#Mann= 3 , 0 , 0
       0      .1       0   434.3    .045       0   444.3      .1       0
Bank Sta=434.3,444.3
XS Rating Curve= 0 ,0
Exp/Cntr=0.3,0.1

Type RM Length L Ch R = 1 ,2545.6  ,193.4,187.6,182.1
XS GIS Cut Line= 2
     1762679.113      125091.733     1762439.248      125346.198
#Sta/Elev= 29
       0  1472.5      10  1472.5      30 1463.66      40 1459.32      50 1455.13
    59.9 1451.43    69.9 1449.21    79.9 1449.49    89.9 1450.35    99.9 1449.76
   109.9 1446.25   119.9 1440.78   129.9 1435.07   149.9 1422.34   154.9 1421.02
   159.9 1419.71   164.9 1420.67   169.9 1421.64   179.8 1427.06   189.8 1432.43
   199.8 1436.88   209.8 1440.88   259.8 1460.36   279.8  1468.6   299.7 1477.14
   319.7 1485.96   329.7 1490.56   339.7 1495.31   349.7 1500.21
#Mann= 3 , 0 , 0
       0      .1       0   154.9    .045       0   164.9      .1       0
Bank Sta=154.9,164.9
XS Rating Curve= 0 ,0
Exp/Cntr=0.3,0.1

Type RM Length L Ch R = 1 ,2358    ,317.8,317.9,317.6
XS GIS Cut Line= 2
     1762488.838      124965.122     1762350.784      125236.549
#Sta/Elev= 30
     9.8 1461.13    19.6 1454.29    29.5 1448.27    39.3 1444.84    58.9 1444.16
    68.8  1441.7    78.6 1437.85    88.4 1433.52   108.1 1424.62   117.9 1419.88
   127.7  1414.4   137.5 1409.47   147.3 1406.44   152.2 1406.26   157.2 1406.08
   162.2 1407.19     167 1408.27   176.8 1412.21   186.6 1416.33   196.5 1419.47
   206.3 1422.45   216.1 1425.57   225.9 1428.92   235.8 1432.51   245.6 1436.35
   255.4  1440.5   265.2 1445.19     275 1450.32   284.9 1455.79   304.5 1467.09
#Mann= 3 , 0 , 0
       0      .1       0   152.2    .045       0   162.2      .1       0
Bank Sta=152.2,162.2
XS Rating Curve= 0 ,0
Exp/Cntr=0.3,0.1

Type RM Length L Ch R = 1 ,2040.1  ,93.7,94.4,95.3
XS GIS Cut Line= 2
     1762213.964      124844.636     1762091.173      125092.231
#Sta/Elev= 30
     9.9 1438.35    19.7 1437.88    29.6 1437.28    39.5  1436.2    49.4 1434.09
    59.2  1430.4    69.1 1425.43      79 1420.03    88.8 1414.32    98.7 1408.72
   108.6 1403.05   118.4  1397.1   128.3    1393   133.2 1392.69   138.2 1392.37
   143.2 1393.34   148.1 1394.29   157.9 1397.61   167.8 1401.26   177.7 1404.52
   187.5 1407.44   197.4 1410.42   207.3 1413.78   217.1 1418.48     227 1424.81
   236.9 1431.36   246.8 1437.56   256.6 1443.55   266.5 1449.53   276.4 1455.61
#Mann= 3 , 0 , 0
       0      .1       0   133.2    .045       0   143.2      .1       0
Bank Sta=133.2,143.2
XS Rating Curve= 0 ,0
Exp/Cntr=0.3,0.1

Type RM Length L Ch R = 1 ,1945.7  ,125.3,128.2,131.2
XS GIS Cut Line= 2
     1762128.468      124839.354     1762005.407      125061.489
#Sta/Elev= 29
       0 1426.55     9.8 1426.55    19.5 1425.09    29.3 1423.62    39.1 1422.02
    48.8 1419.83    58.6 1416.75    68.4 1412.98    78.1 1409.14    87.9 1405.46
    97.7 1401.85   107.4  1397.7   117.2 1392.64     127 1388.54   131.7 1388.32
   136.7 1388.08   141.7 1389.56   146.5 1390.98   156.3 1395.37     166 1399.72
   175.8 1403.79   185.6 1407.87   195.3  1412.2   205.1  1416.8   214.9 1422.03
   224.6 1427.69   234.4 1433.58   244.2 1439.41   253.9 1444.97
#Mann= 3 , 0 , 0
       0      .1       0   131.7    .045       0   141.7      .1       0
Bank Sta=131.7,141.7
XS Rating Curve= 0 ,0
Exp/Cntr=0.3,0.1

Type RM Length L Ch R = 1 ,1817.5  ,345.2,345,344.7
XS GIS Cut Line= 2
      1762037.24      124782.611     1761875.787      124997.881
#Sta/Elev= 29
      10 1413.22    19.9 1412.89    29.9 1413.11    39.9 1411.95    49.8 1409.52
    59.8 1406.28    69.8 1402.23    79.7 1397.64    89.7  1392.7    99.7 1387.32
   109.6 1381.54   114.6 1379.51   119.6 1377.48   124.6 1377.68   129.6 1377.89
   139.5 1381.13   149.5 1385.81   159.5 1390.66   169.4 1395.69   179.4 1400.39
   189.4 1405.03   199.3 1409.38   209.3 1413.53   219.3 1417.46   229.2 1421.62
   239.2  1425.7   249.2 1429.92   259.1 1434.03   269.1 1438.05
#Mann= 3 , 0 , 0
       0      .1       0   114.6    .045       0   124.6      .1       0
Bank Sta=114.6,124.6
XS Rating Curve= 0 ,0
Exp/Cntr=0.3,0.1

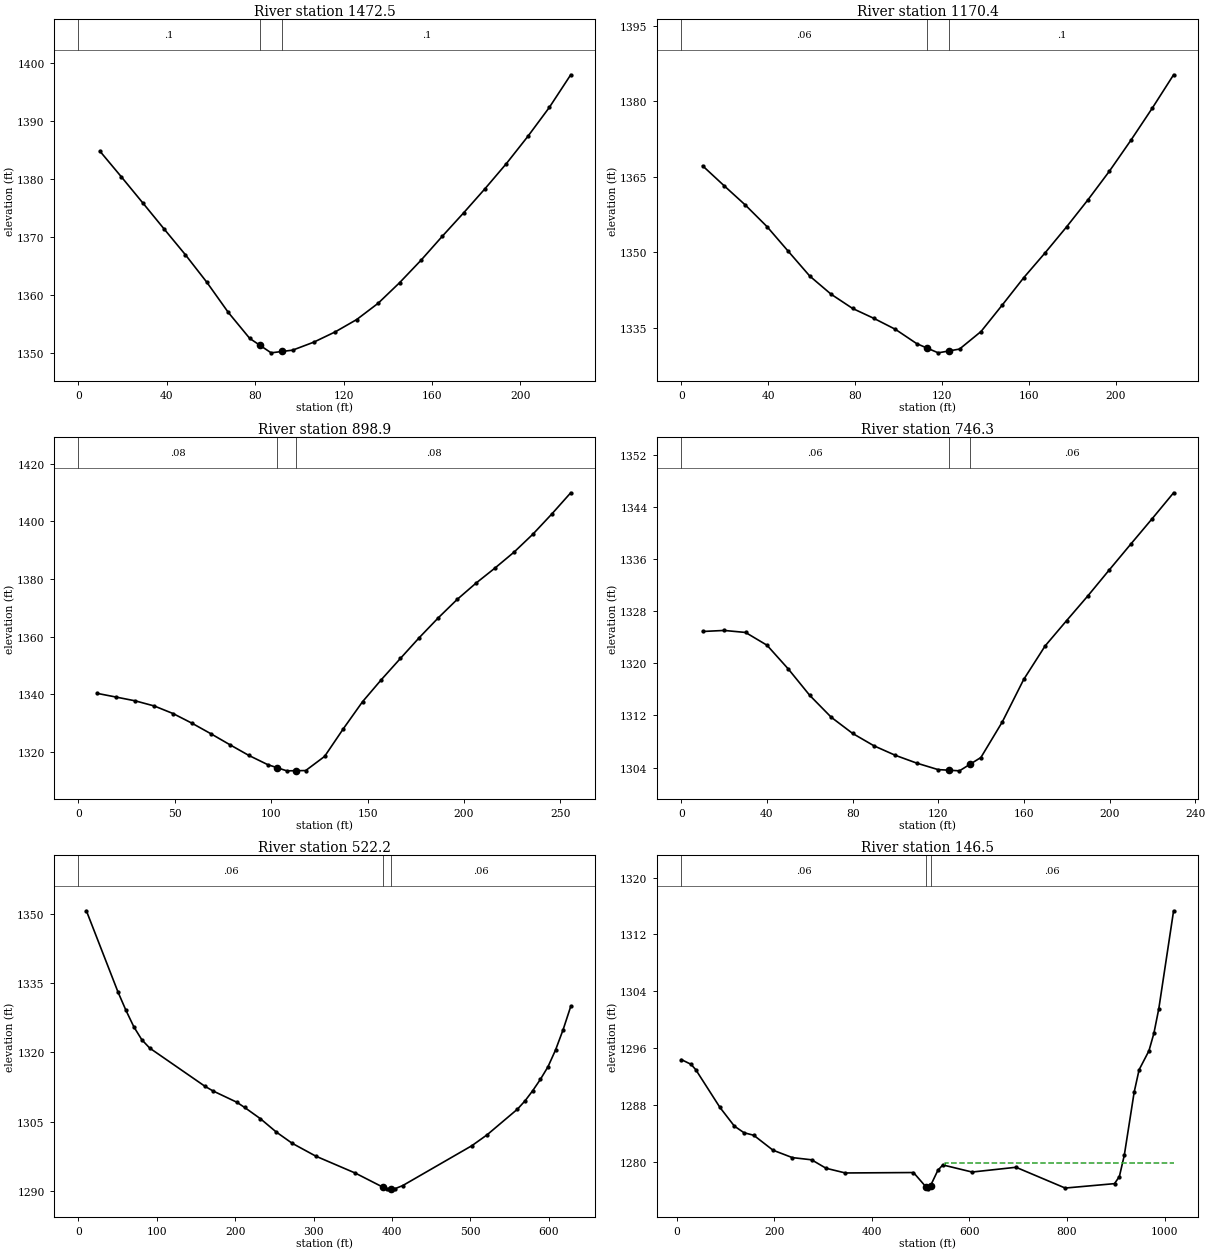
Type RM Length L Ch R = 1 ,1472.5  ,307.7,302.1,296.5
XS GIS Cut Line= 2
     1761754.113      124586.061      1761623.08      124766.232
#Sta/Elev= 25
     9.7 1384.81    19.4 1380.39    29.1  1375.9    38.7 1371.43    48.4 1366.96
    58.1 1362.22    67.8 1357.03    77.5 1352.55    82.2 1351.34    87.2 1350.06
    92.2  1350.3    96.9 1350.52   106.5  1351.9   116.2 1353.67   125.9 1355.79
   135.6 1358.59   145.3 1362.13     155    1366   164.7 1370.16   174.4 1374.21
     184 1378.34   193.7 1382.68   203.4 1387.36   213.1 1392.34   222.8 1397.97
#Mann= 3 , 0 , 0
       0      .1       0    82.2    .045       0    92.2      .1       0
Bank Sta=82.2,92.2
XS Rating Curve= 0 ,0
Exp/Cntr=0.3,0.1

Type RM Length L Ch R = 1 ,1170.4  ,277.5,271.5,265.5
XS GIS Cut Line= 2
     1761478.007       124398.87      1761400.79        124611.8
#Sta/Elev= 25
     9.8  1367.2    19.7 1363.24    29.5 1359.39    39.4 1355.13    49.2 1350.22
    59.1 1345.29    68.9 1341.69    78.8 1338.86    88.6 1336.89    98.5 1334.71
   108.3 1331.87   113.2 1330.96   118.2 1330.04   123.2 1330.42     128 1330.79
   137.9 1334.28   147.7 1339.56   157.6    1345   167.4 1349.92   177.3 1355.09
   187.1 1360.45     197 1366.16   206.8 1372.25   216.7 1378.67   226.5 1385.29
#Mann= 3 , 0 , 0
       0     .06       0   113.2    .045       0   123.2      .1       0
Bank Sta=113.2,123.2
XS Rating Curve= 0 ,0
Exp/Cntr=0.3,0.1

Type RM Length L Ch R = 1 ,898.9   ,151.7,152.6,153.6
XS GIS Cut Line= 2
     1761180.841      124340.373     1761166.802       124595.42
#Sta/Elev= 28
     9.8 1340.31    19.6 1339.03    29.5 1337.72    39.3 1335.95    49.1 1333.31
    58.9 1329.96    68.8 1326.27    78.6 1322.48    88.4 1318.78    98.2 1315.58
   103.1 1314.51   108.1 1313.43   113.1 1313.48   117.9 1313.53   127.7 1318.44
   137.5 1328.12   147.4 1337.44   157.2 1345.13     167 1352.43   176.8 1359.66
   186.7 1366.56   196.5 1372.95   206.3 1378.62   216.1 1383.83     226 1389.36
   235.8 1395.61   245.6 1402.61   255.4 1409.96
#Mann= 3 , 0 , 0
       0     .08       0   103.1    .045       0   113.1     .08       0
Bank Sta=103.1,113.1
XS Rating Curve= 0 ,0
Exp/Cntr=0.3,0.1

Type RM Length L Ch R = 1 ,746.3   ,224.4,224,223.7
XS GIS Cut Line= 2
     1761036.468      124338.615     1761013.247      124567.339
#Sta/Elev= 25
      10 1324.91      20 1325.07      30 1324.76      40  1322.8      50 1319.13
      60 1315.08      70 1311.73      80 1309.24      90 1307.33     100 1305.87
     110 1304.67   119.9 1303.68   124.9 1303.59   129.9 1303.49   134.9 1304.52
   139.9 1305.54   149.9 1311.01   159.9 1317.54   169.9 1322.69   179.9 1326.57
   189.9  1330.4   199.9 1334.39   209.9 1338.34   219.9 1342.25   229.9 1346.23
#Mann= 3 , 0 , 0
       0     .06       0   124.9    .045       0   134.9     .06       0
Bank Sta=124.9,134.9
XS Rating Curve= 0 ,0
Exp/Cntr=0.3,0.1

Type RM Length L Ch R = 1 ,522.2   ,378.8,375.7,372.6
XS GIS Cut Line= 4
     1761070.047      124161.079     1760811.209      124354.577
     1760801.417      124464.957     1760935.178      124605.945
#Sta/Elev= 30
    10.1  1350.7    50.5 1333.07    60.6 1329.12    70.7 1325.54    80.8 1322.76
    90.9 1320.94   161.6 1312.64   171.7 1311.65     202 1309.21   212.1 1308.07
   232.3 1305.62   252.5 1302.74   272.7 1300.31     303 1297.51   353.4 1293.84
   388.7 1290.78   393.7 1290.43   398.7 1290.44   403.8 1290.45   413.8 1291.13
     502 1299.77   521.4 1302.12   560.3  1307.7     570 1309.51   579.7 1311.69
   589.5 1314.14   599.2 1316.87   608.9 1320.52   618.6 1324.94   628.3 1329.97
#Mann= 3 , 0 , 0
       0     .06       0   388.7    .045       0   398.7     .06       0
Bank Sta=388.7,398.7
XS Rating Curve= 0 ,0
Exp/Cntr=0.3,0.1

Type RM Length L Ch R = 1 ,146.5   ,73.3,73.4,73.6
XS GIS Cut Line= 4
     1760484.824      123852.243     1760438.687      124235.061
     1760457.937       124554.61     1760539.174      124856.714
#Sta/Elev= 30
     9.9 1294.42    29.7 1293.76    39.5    1293      89  1287.7   118.6 1285.07
   138.4 1284.14   158.2 1283.79   197.7 1281.69   237.3 1280.65   276.8 1280.34
   306.5 1279.15     346 1278.49   485.6 1278.55   510.6 1276.58   515.6 1276.26
   520.6 1276.71   535.6 1278.87   545.7 1279.62   605.7 1278.62   695.7 1279.29
   796.5 1276.37   897.5 1276.99   907.5 1277.99   917.6 1280.99   937.8 1289.85
   947.9 1292.99   968.1 1295.66   978.2 1298.11   988.3 1301.58  1018.6 1315.33
#Mann= 3 , 0 , 0
     9.9     .06       0   510.6    .045       0   520.6     .06       0
#XS Ineff= 2 , 0
                          549.66         1279.96
Permanent Ineff=
       F       F
Bank Sta=510.6,520.6
XS Rating Curve= 0 ,0
Exp/Cntr=0.3,0.1

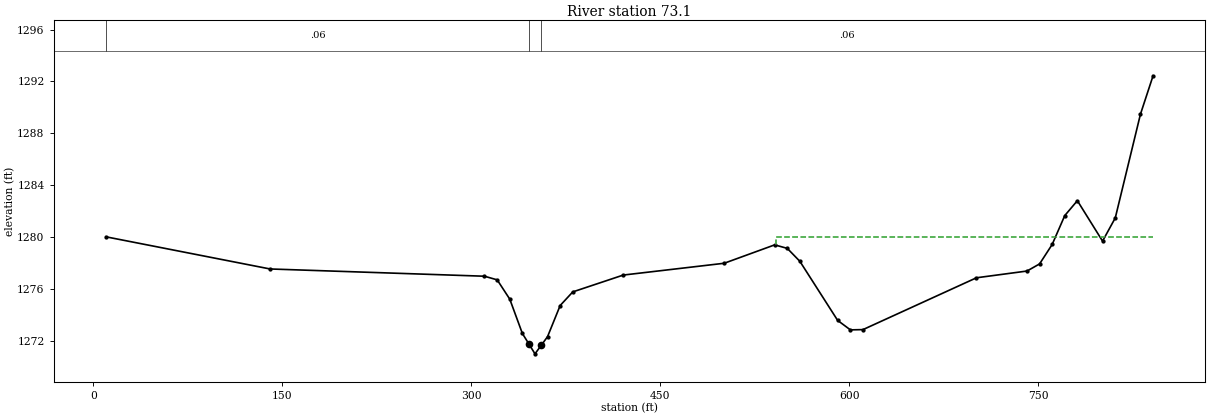
Type RM Length L Ch R = 1 ,73.1    ,72.9,73.1,73.3
XS GIS Cut Line= 2
     1760354.861      124017.468     1760399.319      124857.488
#Sta/Elev= 30
      10 1280.01   140.2 1277.53   310.4 1276.97   320.5 1276.69   330.5  1275.2
   340.5 1272.55   345.5 1271.77   350.5 1270.98   355.5 1271.64   360.5 1272.31
   370.5 1274.71   380.5 1275.76   420.6 1277.06   500.7 1277.97   540.8 1279.39
   550.8 1279.12   560.8 1278.12   590.8 1273.56   600.9 1272.83   610.9 1272.85
     701 1276.85   741.1 1277.37   751.1 1277.92   761.1 1279.42   771.1 1281.65
   781.1  1282.8   801.1 1279.68   811.2 1281.47   831.2 1289.48   841.2 1292.44
#Mann= 3 , 0 , 0
      10     .06       0   345.5    .045       0   355.5     .06       0
#XS Ineff= 2 , 0
                          541.95         1279.96
Permanent Ineff=
       F       F
Bank Sta=345.5,355.5
XS Rating Curve= 0 ,0
Exp/Cntr=0.3,0.1
Stream Node=Threefork Branch,Main            , 0 , 0 ,Upstream end
Stream Node=Threefork Branch,Main            , 0 , 1 ,Downstream end

Chan Stop Cuts=-1
Use User Specified Reach Order=0